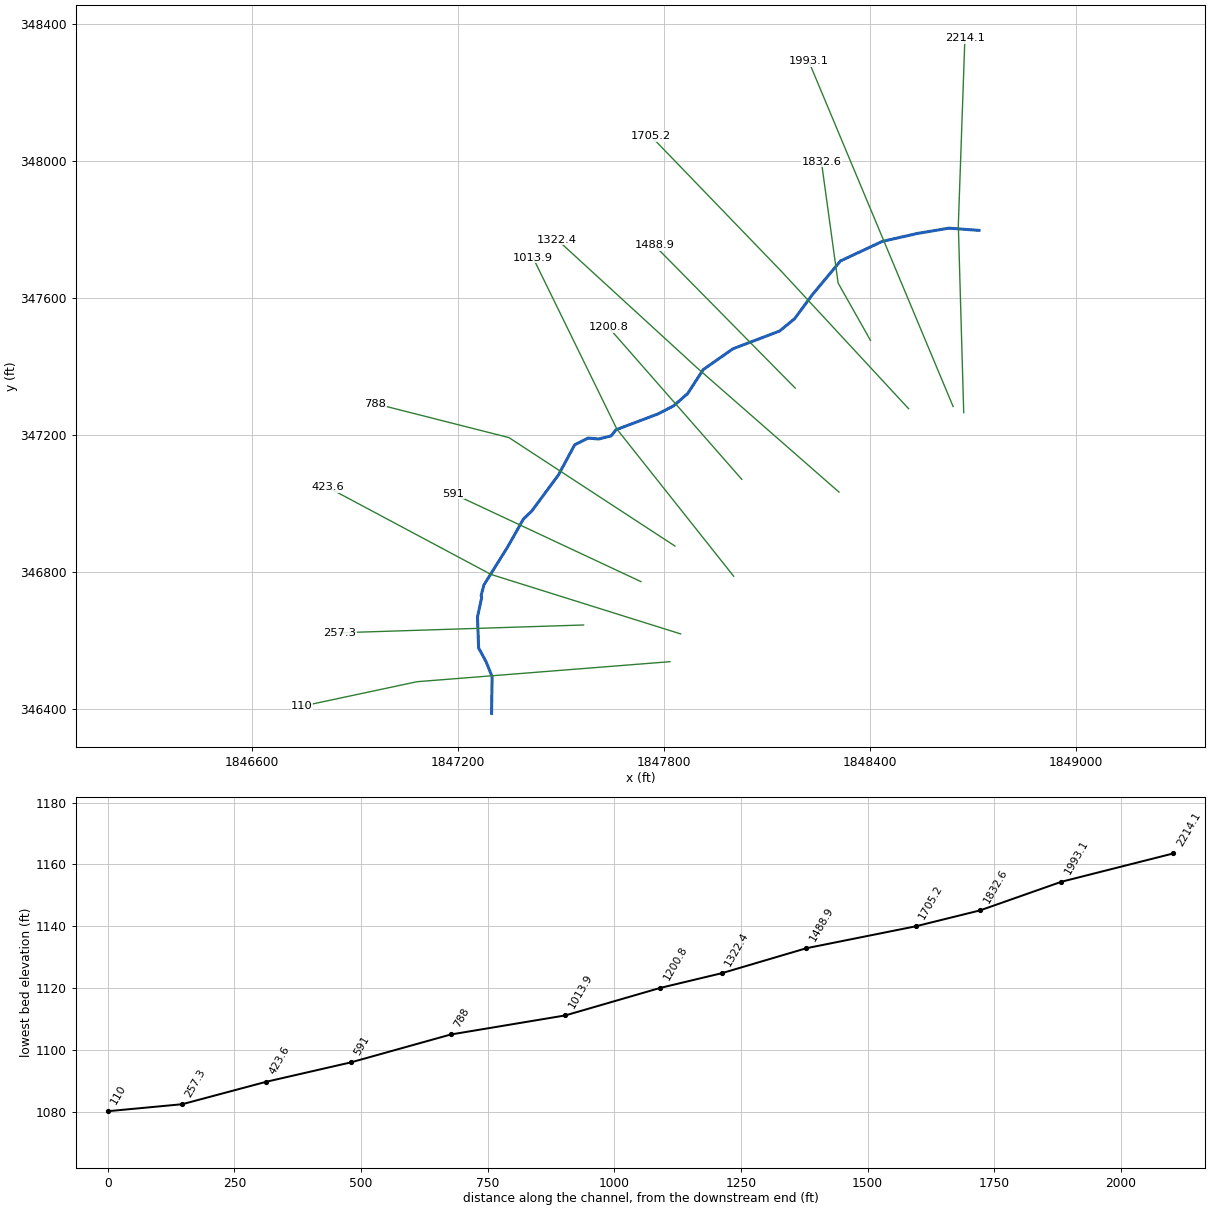
--- LngBrnch.prj (project) ---

Proj Title=LngBrnch
Current Plan=p01
Default Exp/Contr=0,0
English Units
Geom File=g01
Flow File=f01
Plan File=p01
BEGIN DESCRIPTION:
END DESCRIPTION:
DSS Export Rating Curves= 0
DSS Export Rating Curve Sorted= 0
DSS Export Volume Flow Curves= 0
DXF OffsetX= 0
DXF OffsetY= 0
DXF ScaleX= 0
DXF ScaleY= 0

--- LngBrnch.p01 (plan) ---

Plan Title=Floodplain
Program Version=4.00
Geom File=g01
Flow File=f01
K Sum by GR=0
Std Step Tol=0.01
Critical Tol=0.01
Num of Std Step Trials=20
Max Error Tol=0.3
Flow Tol Ratio=0.001
Split Flow NTrial=30
Split Flow Tol=0.02
Split Flow Ratio=0.02
Log Output Level=0
Friction Slope Method=1
Unsteady Friction Slope Method=2
Unsteady Bridges Friction Slope Method=1
Global Log Level=0
CheckData=False
Run HTab=0
Run UNet=0
Run PostProcess=0
UNET Theta=0
UNET Theta Warmup=0
UNET ZTol=0
UNET ZSATol=0
UNET MxIter=0
UNET MaxInSteps=0
UNET DtIC=0
UNET DtMin=0
UNET MaxCRTS=0
UNET WFStab=0
UNET SFStab=0
UNET WFX=0
UNET SFX=0
UNET DSS MLevel=0
UNET DZMax Abort=0
UNET Convert EG Bridges=0
UNET Use Existing IB Tables=0
UNET Froude Limit=0
UNET Froude Power=0
Write IC File=0
Echo Input=False
Echo Output=False
Write Detailed=0

--- LngBrnch.f01 (steady flow) ---

Flow Title=NFF Regression Equation
Program Version=4.00
Number of Profiles=1
Profile Names=P100yr
River Rch & RM=LngBrnch,Main      ,2214.1
944.7448
River Rch & RM=LngBrnch,Main      ,257.3
982.1868
Boundary for River Rch & Prof#=LngBrnch,Main      ,1
Up Type=0
Dn Type=3
Dn Slope=0.032683

--- LngBrnch.g01 (geometry) ---

Geom Title=USGS 3m DEM
Program Version=4.10

River Reach=LngBrnch        ,Main
Reach XY= 30
     1848718.117      347797.482      1848630.09      347803.955
      1848538.18      347788.421     1848435.913       347765.12
      1848314.23      347708.161     1848231.381      347608.484
     1848180.895      347539.875     1848136.882      347503.629
     1848000.958      347451.848     1847914.226      347391.006
     1847868.918      347321.103     1847827.494      347284.856
     1847782.186      347261.555     1847660.084      347215.423
     1847645.879      347197.497     1847609.409       347188.38
     1847579.163      347191.216     1847539.655      347171.462
     1847492.584      347083.814     1847414.675      346978.311
      1847390.14      346954.623     1847344.994      346874.484
     1847275.087      346762.437     1847266.971      346731.598
     1847268.642      346725.473      1847256.42      346668.692
     1847259.798      346578.276     1847281.337      346538.881
     1847299.071      346494.546     1847297.471       346387.57

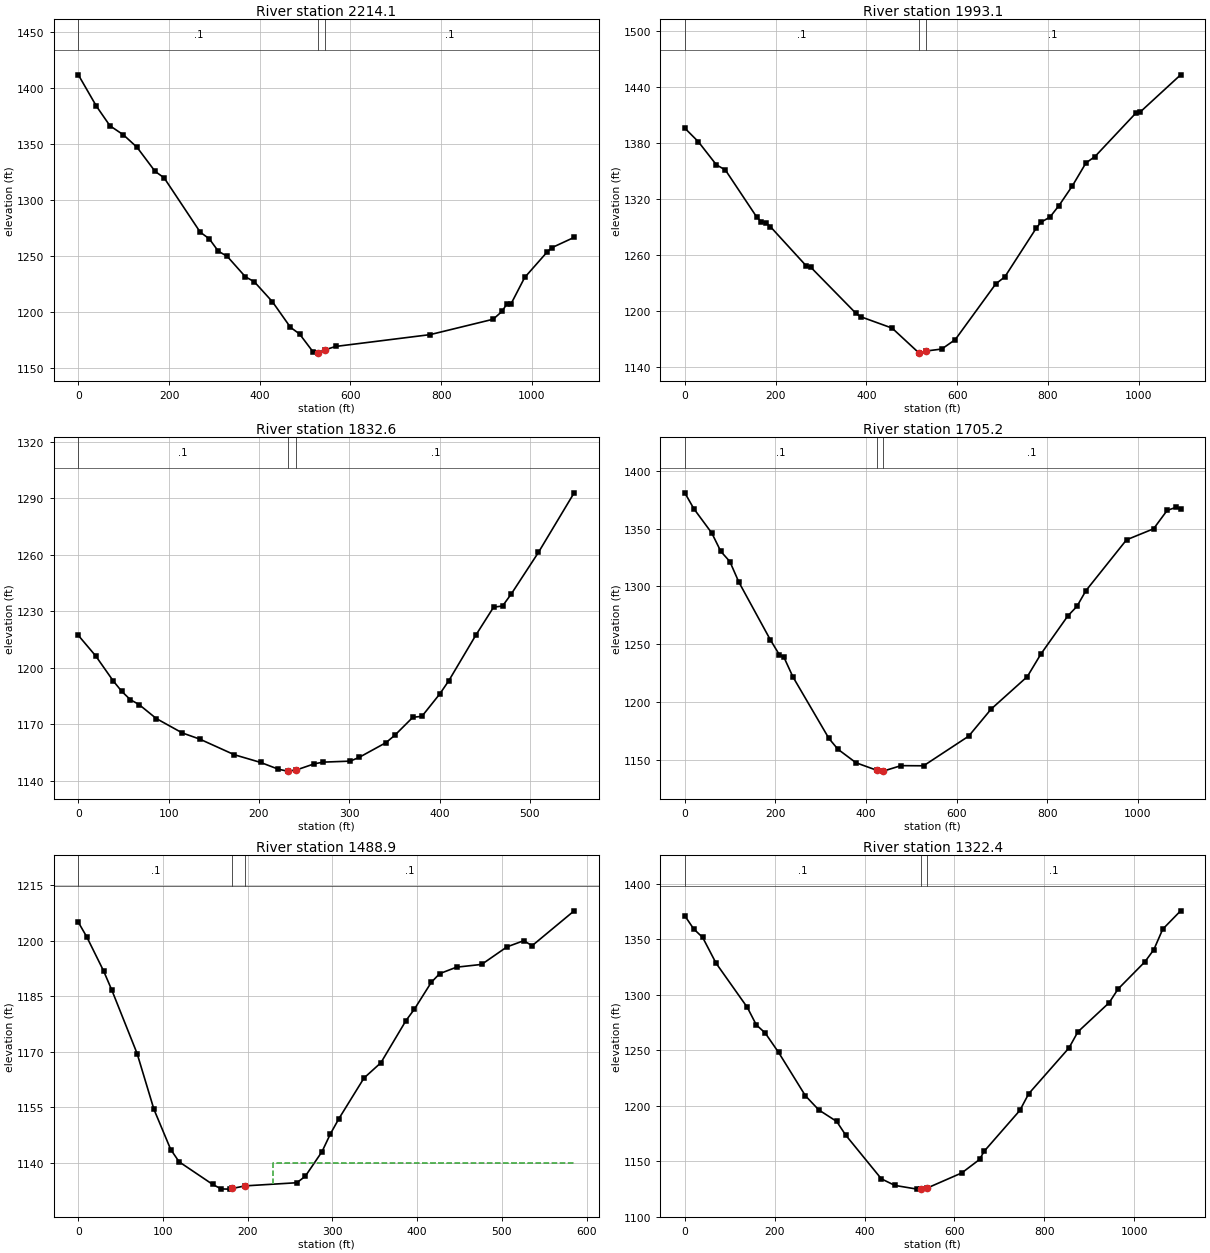
Type RM Length L Ch R = 1 ,2214.1  ,212.7,221,230.1
XS GIS Cut Line= 3
     1848673.446      347265.459     1848657.738      347812.582
     1848676.855      348358.009
#Sta/Elev= 30
       0 1411.55    39.8 1383.64    69.7 1366.14    99.5 1358.03   129.4 1346.97
   169.2 1325.52   189.1 1319.77   268.7 1271.34   288.6 1265.44   308.5 1254.43
   328.4 1249.72   368.2 1231.61   388.1 1227.07   427.9 1209.32   467.7 1186.52
   487.6 1180.65   517.5 1164.64   527.4 1163.54   529.2 1163.84   544.2 1166.53
   567.2 1169.49   775.6 1180.03   914.5 1193.73   934.3 1200.82   944.3 1207.22
   954.2 1207.64     984 1230.94  1033.6 1253.68  1043.5 1257.43  1093.1  1266.7
#Mann= 3 , 0 , 0
       0      .1       0   529.2    .045       0   544.2      .1       0
Bank Sta=529.2,544.2
XS Rating Curve= 0 ,0
Exp/Cntr=0.3,0.1

Type RM Length L Ch R = 1 ,1993.1  ,170.1,160.5,150.9
XS GIS Cut Line= 3
     1848642.518      347283.322     1848432.136      347787.163
     1848221.754      348291.003
#Sta/Elev= 30
       0 1395.49    29.8 1380.96    69.5 1356.21    89.4 1350.61   158.8 1299.91
   168.8 1295.04   178.7  1294.1   188.6 1289.85     268 1247.59     278 1246.15
   377.2  1196.9   387.2 1193.41   456.6 1181.18   515.8  1154.5   516.2 1154.37
   530.8  1156.6   565.8 1158.74   595.6 1168.83     685 1228.65   704.8 1236.06
   774.3 1288.54   784.2 1294.61   804.1 1300.11     824 1312.44   853.8 1333.79
   883.5  1358.2   903.4 1365.06   992.7 1411.26  1002.6 1412.62    1092 1452.63
#Mann= 3 , 0 , 0
       0      .1       0   515.8    .045       0   530.8      .1       0
Bank Sta=515.8,530.8
XS Rating Curve= 0 ,0
Exp/Cntr=0.3,0.1

Type RM Length L Ch R = 1 ,1832.6  ,109.8,127.4,144.9
XS GIS Cut Line= 3
     1848401.529      347476.608     1848307.389      347643.789
     1848258.695      347997.628
#Sta/Elev= 30
       0 1217.21    19.2 1206.33    38.4 1193.19      48 1187.52    57.6 1183.06
    67.2 1180.49    86.3 1173.05   115.1  1165.4   134.3 1162.15   172.7 1153.82
   201.8 1149.73   221.6 1146.11   231.6 1145.11   241.5 1145.74   261.3    1149
   271.2 1149.89     301 1150.42   310.9 1152.41   340.7 1160.26   350.6 1164.24
   370.4 1173.72   380.4  1174.2   400.2  1186.1   410.1 1193.06   439.9 1217.16
   459.8 1232.21   469.7 1232.82   479.6 1239.37   509.4 1261.26     549 1292.94
#Mann= 3 , 0 , 0
       0      .1       0   231.6    .045       0   241.5      .1       0
Bank Sta=231.6,241.5
XS Rating Curve= 0 ,0
Exp/Cntr=0.3,0.1

Type RM Length L Ch R = 1 ,1705.2  ,214.4,215.6,216.8
XS GIS Cut Line= 3
     1848512.696      347277.082     1848141.462      347678.497
     1847761.763       348072.75
#Sta/Elev= 30
       0 1381.04    19.9  1367.3    59.6 1346.17    79.5 1330.29    99.4 1321.52
   119.3 1303.66   188.9 1253.62   208.8  1240.7   218.7 1238.65   238.6 1221.59
   318.1 1168.23     338 1158.88   377.8  1147.2   423.3 1140.75   437.4 1139.95
   438.3 1140.01   477.2  1144.7   526.9 1144.57   626.4 1170.25   676.1 1193.75
   755.8 1221.84   785.6 1241.28   845.3 1274.45   865.2 1282.62   885.1 1296.26
   974.7 1340.33  1034.4 1349.88  1064.3 1365.79  1084.2 1368.51  1094.1 1366.71
#Mann= 3 , 0 , 0
       0      .1       0   423.3    .045       0   438.3      .1       0
Bank Sta=423.3,438.3
XS Rating Curve= 0 ,0
Exp/Cntr=0.3,0.1

Type RM Length L Ch R = 1 ,1488.9  ,166,167.2,168.2
XS GIS Cut Line= 2
     1848182.409       347337.02      1847771.76      347754.161
#Sta/Elev= 30
       0 1204.98     9.9 1201.05    29.8 1191.84    39.7 1186.55    69.4  1169.5
    89.3  1154.4   109.1 1143.56     119 1140.24   158.7 1134.12   168.7 1132.91
   178.6 1132.86     182 1133.05     197 1133.74     258 1134.59   267.9 1136.32
   287.7 1142.99   297.6 1147.79   307.6 1151.89   337.3 1162.89   357.2 1167.01
   386.9 1178.43   396.8  1181.5   416.7 1188.74   426.6 1191.09   446.5 1192.84
   476.2 1193.59     506 1198.32   525.8 1199.99   535.8 1198.65   585.4 1208.07
#Mann= 3 , 0 , 0
       0      .1       0     182    .045       0     197      .1       0
#XS Ineff= 2 , 0
                          230.41         1139.94
Permanent Ineff=
       F       F
Bank Sta=182,197
XS Rating Curve= 0 ,0
Exp/Cntr=0.3,0.1

Type RM Length L Ch R = 1 ,1322.4  ,124.5,121.5,118.7
XS GIS Cut Line= 3
     1848309.948      347033.534      1847898.81       347393.97
     1847488.722      347770.322
#Sta/Elev= 30
       0 1371.04    19.9 1359.15    39.8  1351.5    69.6  1328.3   139.2 1288.45
   159.1 1272.75   178.9 1265.44   208.8 1247.89   268.4 1208.88   298.2 1196.12
     338 1185.76   357.9 1173.53   437.4 1134.05   467.2 1128.14   516.9 1124.77
   524.6 1125.04   539.6 1125.79   616.3 1139.35   656.1 1151.53     666 1158.78
   745.6 1195.68   765.4 1210.76   854.9 1251.95   874.8 1266.49   944.3 1292.71
   964.2 1305.07  1023.8 1329.52  1043.7 1340.47  1063.6 1358.99  1103.4  1375.5
#Mann= 3 , 0 , 0
       0      .1       0   524.6    .045       0   539.6      .1       0
Bank Sta=524.6,539.6
XS Rating Curve= 0 ,0
Exp/Cntr=0.3,0.1

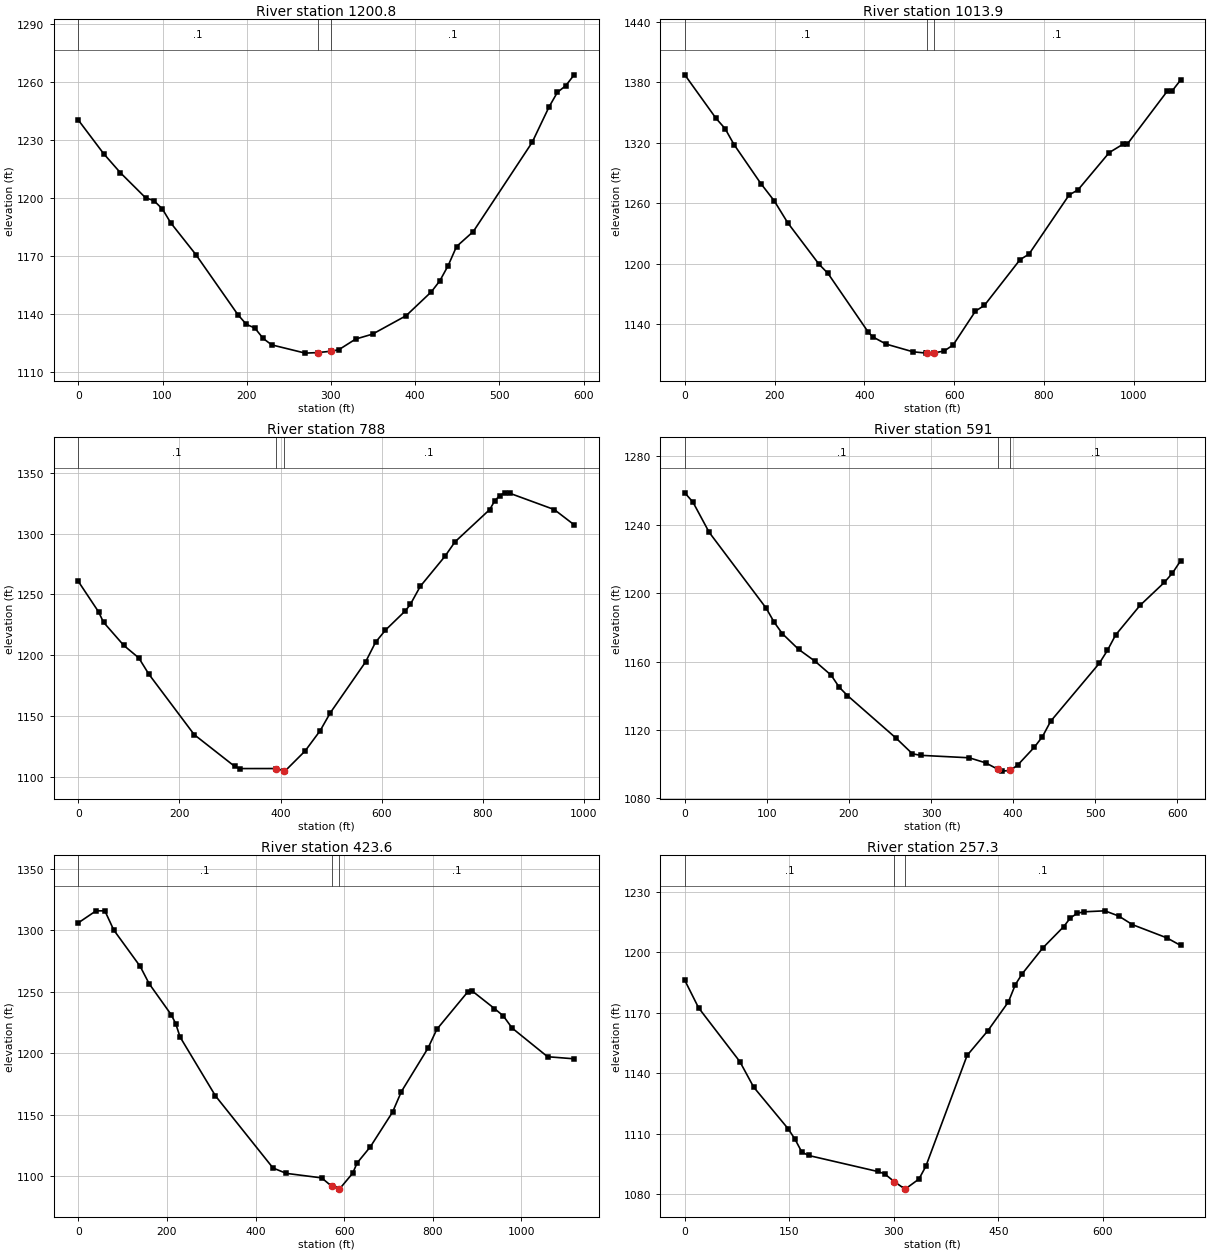
Type RM Length L Ch R = 1 ,1200.8  ,187.7,186.8,181.1
XS GIS Cut Line= 2
     1848026.589      347070.829     1847638.665       347513.94
#Sta/Elev= 30
       0 1240.54      30  1223.2    49.9 1213.32    79.8 1200.37    89.8 1198.84
    99.8 1194.58   109.8 1187.36   139.7 1170.91   189.6 1139.84   199.6 1134.89
   209.6    1133   219.6 1127.59   229.6 1124.29   269.5 1120.01   284.7  1120.3
   299.7 1120.97   309.4 1121.78   329.4 1127.29   349.4 1129.83   389.3 1139.36
   419.2 1151.68   429.2  1157.3   439.2 1165.23   449.2 1175.14   469.1 1182.89
     539 1229.01     559 1247.28     569 1254.91   578.9 1258.31   588.9 1263.94
#Mann= 3 , 0 , 0
       0      .1       0   284.7    .045       0   299.7      .1       0
Bank Sta=284.7,299.7
XS Rating Curve= 0 ,0
Exp/Cntr=0.3,0.1

Type RM Length L Ch R = 1 ,1013.9  ,218.6,226,238.2
XS GIS Cut Line= 3
     1848003.008      346787.832     1847662.549      347217.498
     1847418.391      347717.489
#Sta/Elev= 30
       0 1387.34    69.8    1344    89.7 1333.99   109.6 1318.19   169.4 1279.44
   199.4 1262.18   229.2 1240.56     299 1199.37     319 1190.23   408.7 1131.98
   418.6 1127.29   448.5 1120.09   508.3 1112.46   538.2 1111.13   539.5 1111.15
   554.5 1111.23     578 1113.28   597.9 1119.26   647.6 1152.86   667.4 1158.49
   746.9 1203.92   766.8  1209.4   856.2  1268.1   876.1 1273.21   945.6 1310.19
   975.4 1318.25   985.4 1318.32  1074.8 1371.11  1084.8 1370.86  1104.6  1382.2
#Mann= 3 , 0 , 0
       0      .1       0   539.5    .045       0   554.5      .1       0
Bank Sta=539.5,554.5
XS Rating Curve= 0 ,0
Exp/Cntr=0.3,0.1

Type RM Length L Ch R = 1 ,788     ,193.8,197,200.2
XS GIS Cut Line= 3
     1847831.815      346876.055     1847348.127      347192.563
     1846957.857      347291.756
#Sta/Elev= 30
       0 1260.71    39.9  1235.8    49.8  1227.2    89.7 1208.25   119.6 1197.89
   139.5 1184.54   229.2 1134.92     309 1108.94   318.9 1107.06   391.2 1107.09
   406.2 1105.25   408.6 1104.96   448.5 1121.48   478.4 1138.21   498.3 1152.79
   568.1 1194.58   587.9 1210.76   607.5 1220.74   646.8 1236.54   656.6 1241.76
   676.3 1256.63   725.4 1281.45     745 1293.18   813.8 1319.74   823.6 1326.89
   833.4 1331.09   843.2 1333.43     853 1333.13   941.4 1319.68   980.7 1307.17
#Mann= 3 , 0 , 0
       0      .1       0   391.2    .045       0   406.2      .1       0
Bank Sta=391.2,406.2
XS Rating Curve= 0 ,0
Exp/Cntr=0.3,0.1

Type RM Length L Ch R = 1 ,591     ,164.3,167.3,166.1
XS GIS Cut Line= 2
     1847732.805      346772.176     1847185.815      347028.628
#Sta/Elev= 30
       0 1258.57     9.9 1253.15    29.7 1235.49      99 1191.26   108.9 1182.97
   118.8  1176.3   138.6 1167.14   158.5 1160.23   178.3 1152.01   188.2 1144.96
   198.1 1140.14   257.5 1115.19   277.3 1106.08   287.2 1105.19   346.6 1103.74
   366.4 1100.81   381.7 1096.98   386.2 1095.95   396.7 1096.33     406 1099.71
   425.9 1109.94   435.8 1116.13   445.7 1125.06   505.1    1159     515 1166.58
   524.9  1175.5   554.6 1192.77   584.3 1206.24   594.2 1211.72   604.1 1218.87
#Mann= 3 , 0 , 0
       0      .1       0   381.7    .045       0   396.7      .1       0
Bank Sta=381.7,396.7
XS Rating Curve= 0 ,0
Exp/Cntr=0.3,0.1

Type RM Length L Ch R = 1 ,423.6   ,158.1,165.8,177.6
XS GIS Cut Line= 3
     1847848.367      346619.556     1847295.689      346793.182
     1846819.452      347047.736
#Sta/Elev= 30
       0 1305.93      40 1315.67    59.9 1315.66    79.9 1300.13   139.8 1270.46
   159.8 1256.52   209.8 1231.25   219.7 1224.16   229.7 1213.18   309.6 1165.37
   439.5 1106.81   469.4 1102.46   549.3 1098.79   572.6 1091.81   587.6 1089.68
   589.3 1089.66   619.3 1102.55   629.3 1110.89   659.3 1124.07   709.3 1152.19
   729.3 1168.89   789.3 1204.12   809.3 1219.45   879.3 1249.94   889.3 1250.52
   939.3 1236.33   959.3 1230.36   979.3 1220.45  1059.3 1197.18  1119.3 1195.49
#Mann= 3 , 0 , 0
       0      .1       0   572.6    .045       0   587.6      .1       0
Bank Sta=572.6,587.6
XS Rating Curve= 0 ,0
Exp/Cntr=0.3,0.1

Type RM Length L Ch R = 1 ,257.3   ,146.2,147.2,148.2
XS GIS Cut Line= 2
     1847565.624      346645.573     1846854.699      346622.849
#Sta/Elev= 30
       0  1186.1    19.8 1172.43      79 1145.71    98.8 1133.06   148.2  1112.4
   158.1 1107.18   167.9 1100.78   177.8  1099.1   276.6 1091.17   286.5 1090.04
   300.6 1086.09   315.6 1082.49   316.1  1082.4   335.9 1087.41   345.8 1093.74
     405  1148.8   434.7 1161.03   464.3 1175.41   474.2 1183.96   484.1 1189.37
   513.7 1202.22   543.3 1212.65   553.2 1217.09   563.1 1219.39     573 1220.12
   602.6  1220.6   622.4 1218.04   642.1 1213.75   691.5 1207.18   711.3 1203.42
#Mann= 3 , 0 , 0
       0      .1       0   300.6    .045       0   315.6      .1       0
Bank Sta=300.6,315.6
XS Rating Curve= 0 ,0
Exp/Cntr=0.3,0.1

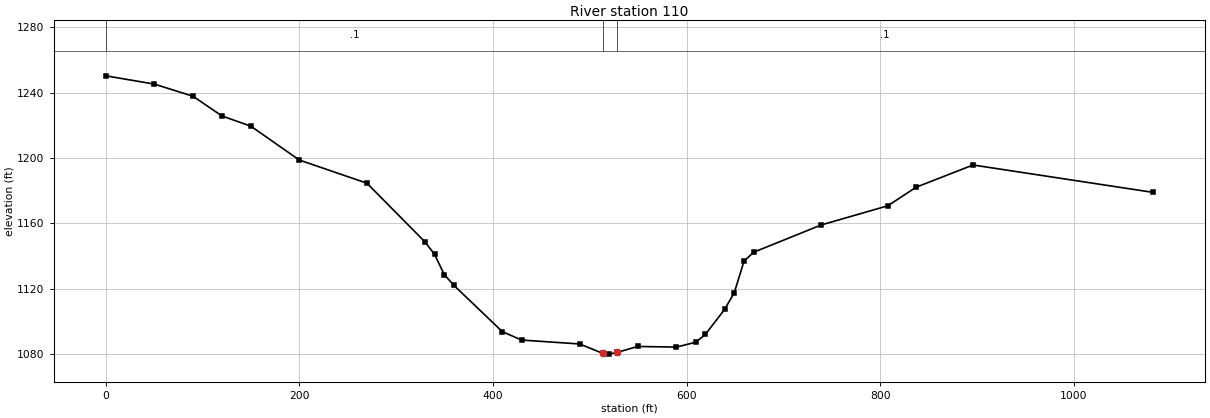
Type RM Length L Ch R = 1 ,110     ,111.9,109.9,107.9
XS GIS Cut Line= 3
     1847817.207      346538.447     1847080.313      346480.015
     1846745.127      346408.475
#Sta/Elev= 30
       0 1250.26      50 1245.21    89.9  1237.8   119.9 1225.73   149.8 1219.47
   199.8 1198.79   269.7 1184.62   329.6 1148.77   339.6 1141.11   349.6 1128.76
   359.6 1122.14   409.6 1093.86   429.5 1088.73   489.5 1086.34   513.4  1080.6
   519.4 1080.13   528.4 1081.21   549.4 1084.82   589.4 1084.43   609.4  1087.4
   619.3 1092.14   639.3  1107.5   649.3 1117.77   659.3 1137.02   669.3 1142.44
   739.2 1159.12   807.8  1170.8   837.1 1182.17   895.9 1195.75  1081.9 1179.01
#Mann= 3 , 0 , 0
       0      .1       0   513.4    .045       0   528.4      .1       0
Bank Sta=513.4,528.4
XS Rating Curve= 0 ,0
Exp/Cntr=0.3,0.1

Chan Stop Cuts=-1
Use User Specified Reach Order=0
Composite Channel Slope=5